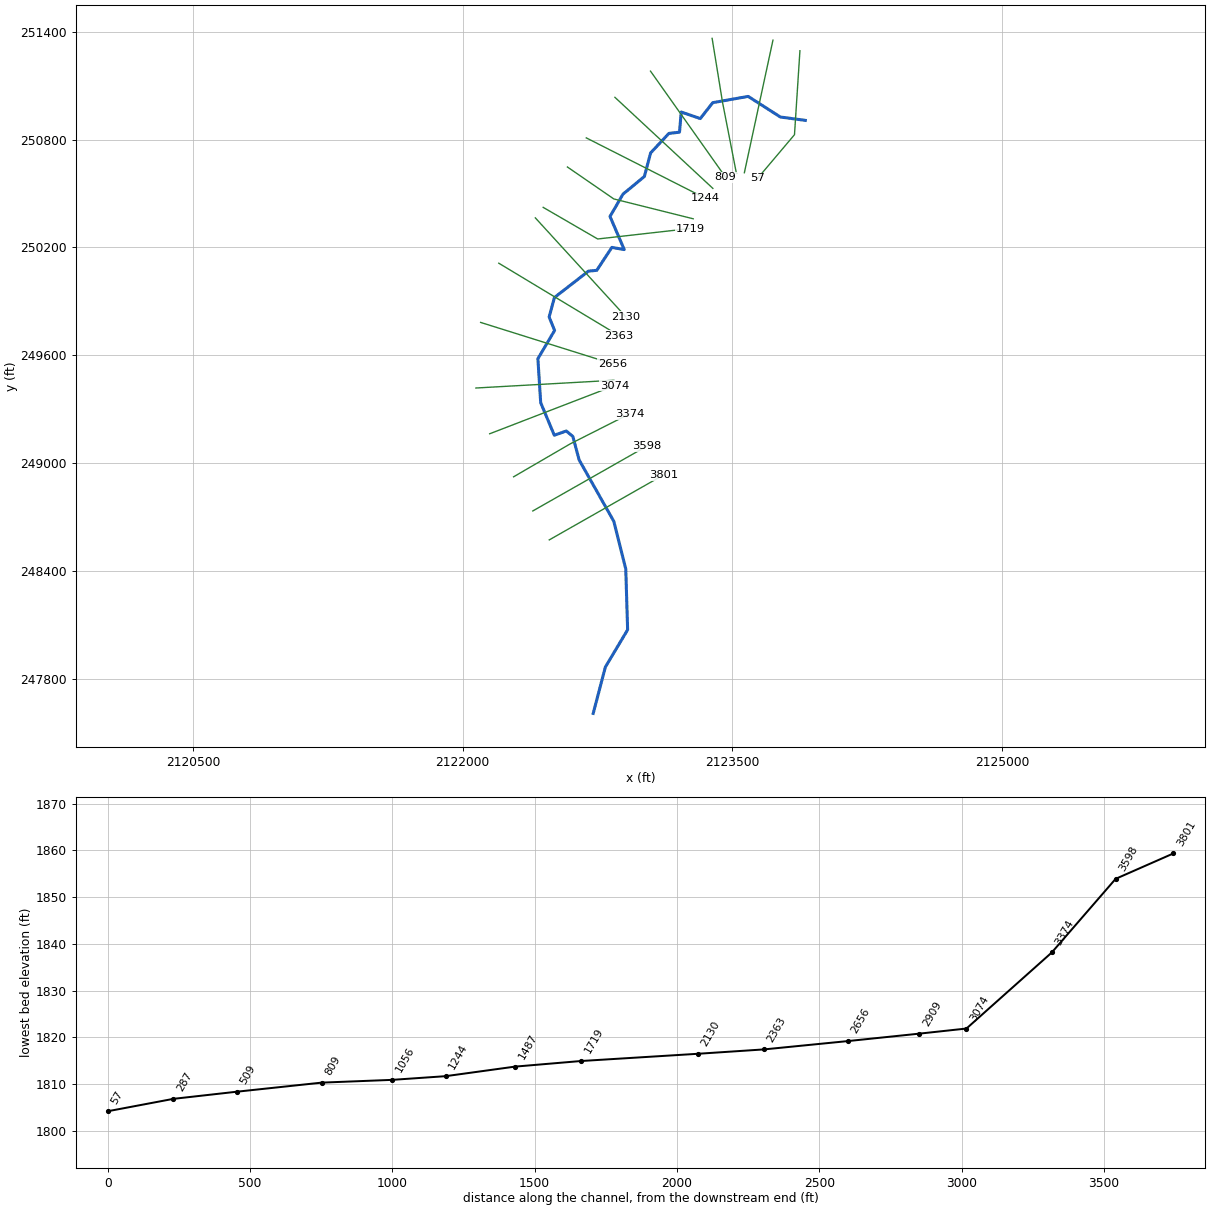
--- SECONDCKT1.prj (project) ---

Proj Title=SECONDCKT1
Current Plan=p01
Default Exp/Contr=0,0
English Units
Geom File=g01
Flow File=f01
Plan File=p01
BEGIN DESCRIPTION:
Stream Name: Second Creek Tributary 1
Flood Zone: Approximate
Monroe County, West Virginia
HEC-RAS Version: 5.0.7
Vertical Datum: NAVD88
Projection: NAD 1983 StatePlane West Virginia S FIPS 4702 (US Feet)
LiDAR: 2016, 1-meter
Land Use: 2016 NLCD
Hydrologic Method:
SIR2010-5033 regression equations
END DESCRIPTION:
DSS Export Rating Curves= 0
DSS Export Rating Curve Sorted= 0
DSS Export Volume Flow Curves= 0
DXF OffsetX= 0
DXF OffsetY= 0
DXF ScaleX= 0
DXF ScaleY= 0

--- SECONDCKT1.p01 (plan) ---

Plan Title=Floodplain
Program Version=5.07
Short Identifier=Floodplain
Geom File=g01
Flow File=f01
Subcritical Flow
K Sum by GR= 0
Std Step Tol= 0.01
Critical Tol= 0.01
Num of Std Step Trials= 20
Max Error Tol= 0.3
Flow Tol Ratio= 0.001
Split Flow NTrial= 30
Split Flow Tol= 0.02
Split Flow Ratio= 0.02
Log Output Level= 0
Friction Slope Method= 1
Unsteady Friction Slope Method= 2
Unsteady Bridges Friction Slope Method= 1
Parabolic Critical Depth
Global Vel Dist= 0 , 0 , 0
Global Log Level= 0
CheckData=False
Encroach Param=-1 ,0,0, 0
Mapping Interval=1HOUR
Computation Time Step Use Courant=        0
Computation Time Step Use Time Series=    0
Computation Time Step Count To Double=0
Computation Time Step Max Doubling=0
Computation Time Step Max Halving=0
Computation Time Step Residence Courant=0
Run HTab= 0
Run UNet= 0
Run Sediment= 0
Run PostProcess= 0
Run WQNet= 0
Run RASMapper=-1
UNET Theta= 0
UNET Theta Warmup= 0
UNET ZTol= 0
UNET ZSATol= 0
UNET MxIter= 0
UNET Max Iter WO Improvement= 0
UNET MaxInSteps= 0
UNET DtIC= 0
UNET DtMin= 0
UNET MaxCRTS= 0
UNET WFStab= 0
UNET SFStab= 0
UNET WFX= 1
UNET SFX= 1
UNET 1D Methodology=Finite Difference
UNET DSS MLevel= 1
UNET Pardiso=0
UNET DZMax Abort= 0
UNET Use Existing IB Tables= 0
UNET Froude Reduction=False
UNET Froude Limit= 0
UNET Froude Power= 0
UNET D1 Cores= 0
UNET D2 Coriolis=0
UNET D2 Cores= 0
UNET D2 Theta= 1
UNET D2 Theta Warmup= 1
UNET D2 Z Tol= 0.01
UNET D2 Volume Tol= 0.01
UNET D2 Max Iterations= 20
UNET D2 Equation= 0
UNET D2 RampUpFraction=0.1
UNET D2 TimeSlices= 1
UNET D2 BCVolumeCheck=0
UNET D1D2 MaxIter= 0
UNET D1D2 ZTol=0.01
UNET D1D2 QTol=0.1
UNET D1D2 MinQTol=1
Write IC File= 0
Write IC File at Fixed DateTime=0
Write IC File at Sim End=0
Echo Input=False
Echo Parameters=False
Echo Output=False
Write Detailed= 0
HDF Write Warmup=0
HDF Write Time Slices=0
HDF Flush=0
HDF Face Node Velocities=0
HDF Compression= 1
HDF Chunk Size= 1
HDF Spatial Parts= 1
HDF Use Max Rows=0
HDF Fixed Rows= 1
Calibration Method= 0
Calibration Iterations= 20
Calibration Max Change=0.05
Calibration Tolerance=0.2
Calibration Maximum=1.5
Calibration Minimum=0.5
Calibration Optimization Method= 1
WQ AD Non Conservative
WQ ULTIMATE=-1
WQ Max Comp Step=1HOUR
WQ Output Interval=15MIN
WQ Output Selected Increments= 0
WQ Output face flow=0
WQ Output face velocity=0
WQ Output face area=0
WQ Output face dispersion=0
WQ Output cell volume=0
WQ Output cell surface area=0
WQ Output cell continuity=0
WQ Output cumulative cell continuity=0
WQ Output face conc=0
WQ Output face dconc_dx=0
WQ Output face courant=0
WQ Output face peclet=0
WQ Output face adv mass=0
WQ Output face disp mass=0
WQ Output cell mass=0
WQ Output cell source sink temp=0
WQ Output nsm pathways=0
WQ Output nsm derived pathways=0
WQ Output MaxMinRange=-1
WQ Daily Max Min Mean=-1
WQ Daily Range=0
WQ Daily Time=0
WQ Create Restart=0
WQ Fixed Restart=0
WQ System Summary=0
WQ Write To DSS=0
WQ Use Fixed Temperature=0
Sorting and Armoring Iterations= 10
XS Update Threshold= 0.02
Bed Roughness Predictor= 0
Hydraulics Update Threshold= 0.02
Energy Slope Method= 1
Volume Change Method= 1
Sediment Retention Method= 0
XS Weighting Method= 0
Number of US Weighted Cross Sections= 1
Number of DS Weighted Cross Sections= 1
Upstream XS Weight=0
Main XS Weight=1
Downstream XS Weight=0
Number of DS XS's Weighted with US Boundary= 1
Upstream Boundary Weight= 1
Weight of XSs Associated with US Boundary= 0
Number of US XS's Weighted with DS Boundary= 1
Downstream Boundary Weight= 0.5
Weight of XSs Associated with DS Boundary= 0.5
Percentile Method= 0
Sediment Output Level= 3
Mass or Volume Output= 0
Output Increment Type= 1
Profile and TS Output Increment= 1
XS Output Flag= 0
XS Output Increment= 10
Write Gradation File= 0
Read Gradation Hotstart= 0
Write HDF5 File= 1
Write Binary Output= 1
Write DSS Sediment File= 0
SV Curve= 0
Specific Gage Flag= 0

--- SECONDCKT1.f01 (steady flow) ---

Flow Title=Flow
Program Version=5.07
Number of Profiles= 6
Profile Names=01pct,10pct,04pct,02pct,0_2pct,01plus
River Rch & RM=SECONDCKT1,Main            ,3801
     561     296     394     475     784     830
River Rch & RM=SECONDCKT1,Main            ,509
     623     330     439     528     869     921
Boundary for River Rch & Prof#=SECONDCKT1,Main            , 1
Up Type= 0
Dn Type= 3
Dn Slope=0.012
DSS Import GetInterval= 0
DSS Import GetPeak= 0
DSS Import FillOption= 0

--- SECONDCKT1.g01 (geometry) ---

Geom Title=Geometry
Program Version=5.07

River Reach=SECONDCKT1      ,Main
Reach XY= 30
2122725.86500002247609.538999983     2122793.573247867.350999992
2122917.27099999248074.3830000182122906.85400002248412.924000017
     2122840.448248677.2470000082122647.74000001249018.392999992
2122612.80100001249149.0359999982122576.34200001249179.417000016
     2122509.502249155.9800000092122433.98100001249336.535999997
     2122418.356249581.327000009     2122511.238249738.445000003
     2122480.856249813.098000019      2122510.37249921.605000014
2122699.60600001250068.305999995     2122745.613250072.647000006
2122829.81500001250200.250999991     2122898.391      250188.098
     2122819.398250372.1260000212122891.44600002250496.257999991
2123010.37000001250594.3479999952123045.09200002250725.423999998
     2123146.655250833.931000018     2123205.683250840.876000001
2123215.23100001250952.855000011     2123321.134250916.397000011
2123390.57900001251004.938000008     2123587.627251039.660000003
2123766.44700002250925.0770000032123905.04753989 250906.46420378

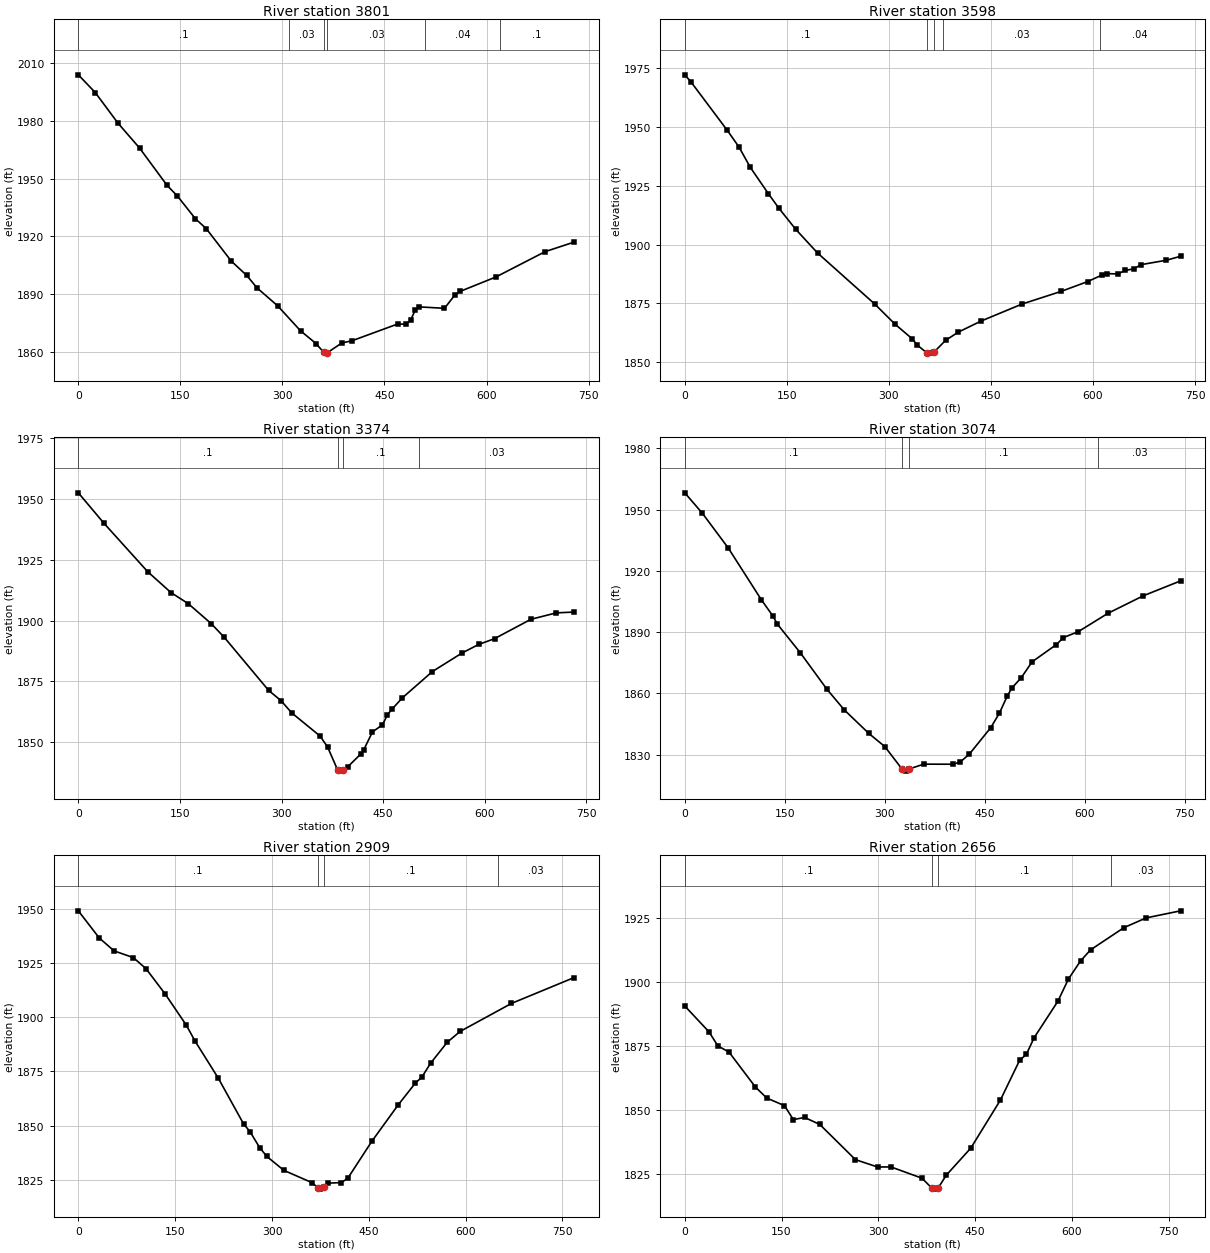
Type RM Length L Ch R = 1 ,3801    ,203.1,203.1,203.1
XS GIS Cut Line= 2
     2122481.572      248574.001     2123115.056      248934.164
#Sta/Elev= 30
       0 2003.92    24.9 1994.71    58.2 1978.85    90.1 1965.84   130.3 1946.55
   145.7 1940.92   172.1 1929.15   188.1 1923.98   224.9 1907.12   247.6 1899.67
   262.6 1893.25   292.9 1883.94   326.8 1870.87   349.3 1864.34   360.8 1859.69
   363.7 1859.34   366.1 1859.57   387.2  1864.6   402.3 1865.77   469.6  1874.5
   481.7 1874.33   488.3 1876.41     495 1881.53   500.4 1883.38   538.2 1882.62
   553.3 1889.47   560.8 1891.36   613.7 1898.89   686.1 1912.06   728.7 1917.02
#Mann= 6 ,-1 , 0
       0      .1       0     310     .03       0   360.8    .045       0
   366.1     .03       0     510     .04       0     620      .1       0
Bank Sta=360.8,366.1
XS Rating Curve= 0 ,0
Exp/Cntr=0.3,0.1

Type RM Length L Ch R = 1 ,3598    ,224.3,224.3,223
XS GIS Cut Line= 2
     2122389.927      248734.848     2123023.411      249095.011
#Sta/Elev= 30
       0 1972.08     9.6 1968.87    62.4 1948.52    79.6 1941.45    96.4 1932.73
   122.8 1921.63   137.9 1915.58   162.9 1906.53   195.1 1896.43   279.3 1874.71
   308.9 1866.22   334.1 1860.03   341.8 1857.27   355.4 1854.12     362  1853.9
   365.9 1854.21   383.2  1859.3   402.1 1862.83   435.7 1867.55   495.8 1874.75
     553  1880.1   592.1 1884.28   613.7 1887.13   620.9 1887.66   636.1 1887.53
   647.4    1889   660.8 1889.76     670 1891.44   707.2 1893.31   728.7 1895.02
#Mann= 5 ,-1 , 0
       0      .1       0   355.4    .045       0   365.9      .1       0
     380     .03       0     610     .04       0
Bank Sta=355.4,365.9
XS Rating Curve= 0 ,0
Exp/Cntr=0.3,0.1

Type RM Length L Ch R = 1 ,3374    ,298.2,299.9,294.8
XS GIS Cut Line= 3
     2122283.352      248924.769     2122597.717      249107.716
     2122926.366      249273.941
#Sta/Elev= 30
       0 1952.57      38 1940.01   102.4 1920.15   136.7 1911.58   162.4 1906.99
     196 1898.84   215.2 1893.25     281 1871.33   299.2 1867.14   315.1 1862.09
   356.9 1852.58   368.1 1848.02   382.8 1838.65   386.5 1838.15   390.2  1838.6
   397.6 1839.87   417.7 1845.37   421.1 1846.73   434.3 1854.29     449 1857.15
   456.4 1861.31   462.7 1863.49   478.4 1868.27   522.8  1879.1   566.6 1886.72
     591 1890.22   614.5 1892.61   668.2 1900.57   705.8 1903.22     732 1903.55
#Mann= 4 ,-1 , 0
       0      .1       0   382.8    .045       0   390.2      .1       0
  503.72     .03       0
Bank Sta=382.8,390.2
XS Rating Curve= 0 ,0
Exp/Cntr=0.3,0.1

Type RM Length L Ch R = 1 ,3074    ,168,165.2,160.7
XS GIS Cut Line= 2
     2122150.441      249164.095     2122844.324      249431.549
#Sta/Elev= 30
       0 1958.26    26.5 1948.18    65.2 1931.22   114.8 1905.87     132 1897.95
     139 1893.85   173.2  1879.9   212.8 1862.16   239.3 1851.85   276.1 1840.33
   300.1 1833.88   325.4 1823.08   332.4 1821.88  336.92 1822.99   358.4  1825.3
   402.7 1825.26   413.3  1826.4     427 1830.29     459 1843.23   471.7 1850.18
   483.6 1858.63   490.6 1862.63   504.7 1867.69   520.9 1875.44   557.4 1883.92
     568 1887.34   590.3 1890.25   634.8 1899.24   687.5 1907.78   743.6 1915.11
#Mann= 4 ,-1 , 0
       0      .1       0   325.4    .045       0  336.92      .1       0
     620     .03       0
Bank Sta=325.4,336.92
XS Rating Curve= 0 ,0
Exp/Cntr=0.3,0.1

Type RM Length L Ch R = 1 ,2909    ,254.1,252.4,247.7
XS GIS Cut Line= 2
     2122073.758      249418.457     2122840.583      249461.474
#Sta/Elev= 30
       0 1948.94    32.5 1936.41    55.5 1930.47    85.1 1927.41   104.8 1922.32
   134.4 1910.69   167.3 1896.28   180.7 1889.01   216.6 1871.99     256 1850.82
   265.9 1847.27     281 1839.86   292.1 1835.82   318.4 1829.43   361.8 1823.79
     371  1821.5   374.3 1820.79   379.8 1821.67   387.4 1823.56   407.1 1823.79
   417.2  1825.7   454.5 1842.74   495.9 1859.74   522.2 1869.66     532  1872.3
   545.6 1878.72   571.4  1888.4   591.4  1893.4   670.9 1906.29     768 1918.21
#Mann= 4 ,-1 , 0
       0      .1       0     371    .045       0   379.8      .1       0
     650     .03       0
Bank Sta=371,379.8
XS Rating Curve= 0 ,0
Exp/Cntr=0.3,0.1

Type RM Length L Ch R = 1 ,2656    ,294,292.8,286.5
XS GIS Cut Line= 2
     2122099.942      249783.166     2122833.102      249553.119
#Sta/Elev= 30
       0 1890.59    37.6 1880.48    51.3 1875.01    68.5 1872.63   109.4 1859.01
     127  1854.7   154.5 1851.74   168.2 1846.29   185.6 1847.14   209.2 1844.41
   264.5 1830.68   298.9 1827.81   319.5 1827.85   367.7 1823.44   383.4 1819.46
   387.1 1819.19   392.4 1819.53   405.3 1824.63   443.3 1835.19   489.2 1853.93
     519 1869.44   529.3  1871.7   541.5 1878.25   578.2 1892.42   594.6  1901.1
   613.5  1908.2     629 1912.49   680.6 1921.13     715 1924.93   768.4 1927.69
#Mann= 4 ,-1 , 0
       0      .1       0   383.4    .045       0   392.4      .1       0
     660     .03       0
Bank Sta=383.4,392.4
XS Rating Curve= 0 ,0
Exp/Cntr=0.3,0.1

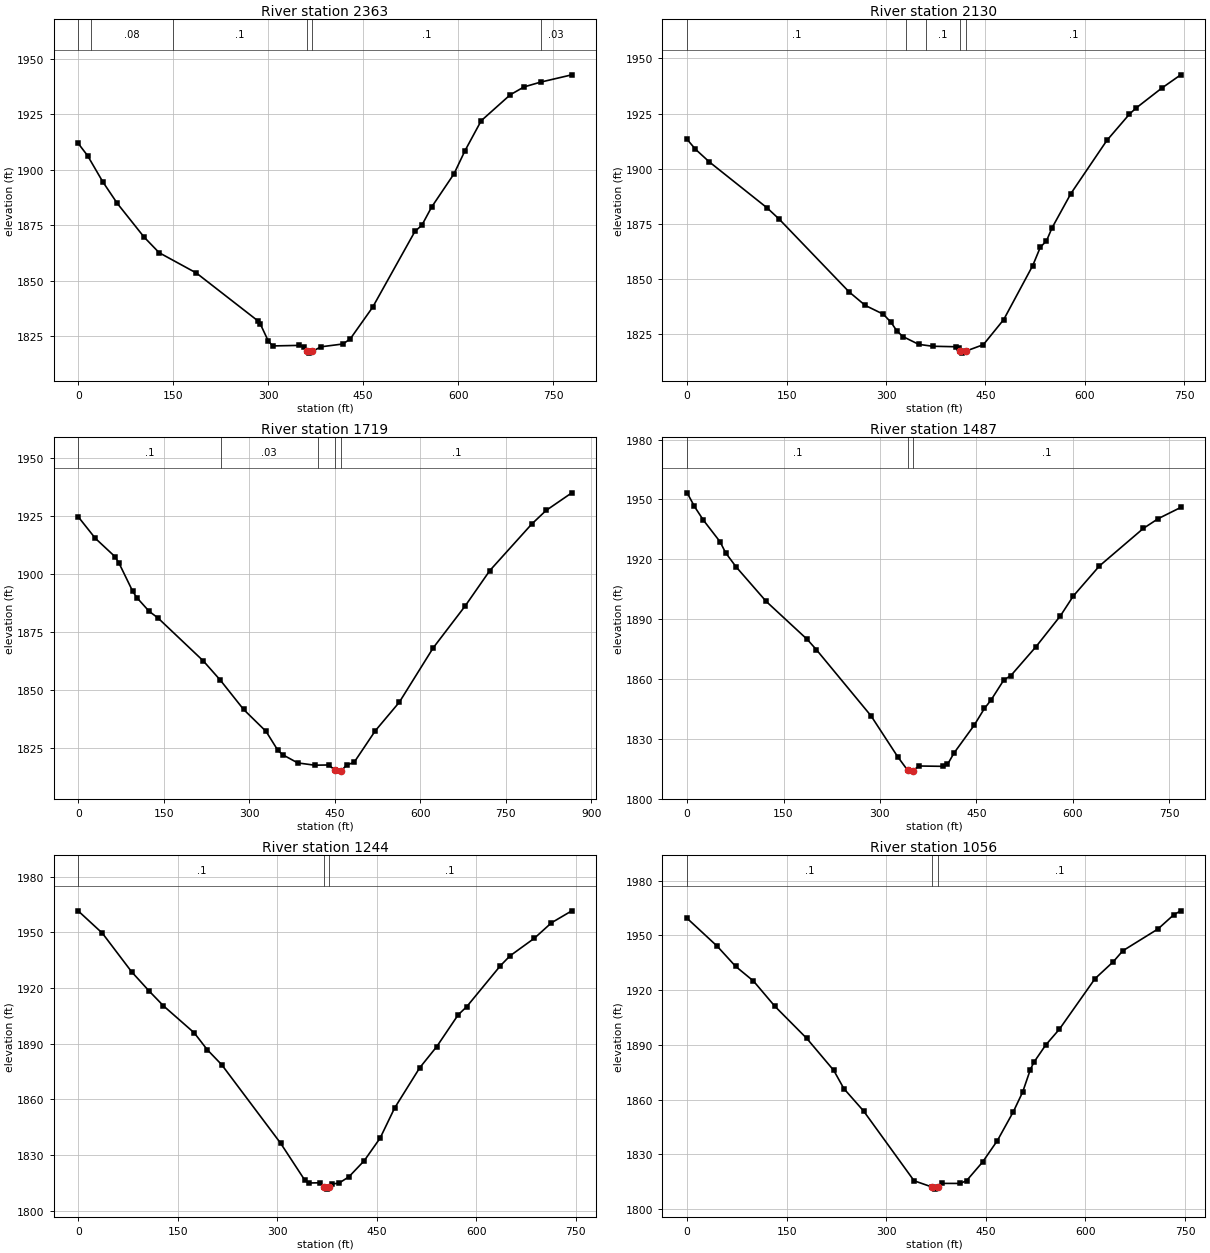
Type RM Length L Ch R = 1 ,2363    ,234.3,233,229.1
XS GIS Cut Line= 2
     2122200.939       250112.34     2122868.638      249710.224
#Sta/Elev= 30
       0 1911.94    14.8 1906.41    38.8 1894.63    61.8 1884.86   103.9 1869.75
   127.8 1862.68   186.5 1853.54   283.2 1832.08   287.8 1830.39   299.9 1823.03
   306.9 1820.66   349.1 1820.91   356.7 1820.37   360.5 1818.31   364.4 1817.42
  369.57 1818.22   383.6 1820.28     418 1821.54   429.5 1823.81   464.8 1838.04
   531.7 1872.28   542.6 1875.04     558 1883.22   593.5 1898.28   610.6 1908.57
   636.3 1922.15   682.2 1933.85   703.9 1937.39     730 1939.55   779.4 1942.85
#Mann= 6 ,-1 , 0
       0      .1       0      20     .08       0     150      .1       0
   360.5    .045       0  369.57      .1       0     730     .03       0
Bank Sta=360.5,369.57
XS Rating Curve= 0 ,0
Exp/Cntr=0.3,0.1

Type RM Length L Ch R = 1 ,2130    ,392.2,411.4,414.8
XS GIS Cut Line= 2
     2122404.023      250364.454     2122906.577      249815.103
#Sta/Elev= 30
       0 1913.29    12.5 1908.86    33.4 1903.12   120.8 1882.23   138.6 1877.25
   244.2 1844.24   268.5 1838.12   295.9 1834.11   307.5 1830.43   316.4 1826.52
   325.3    1824   349.3 1820.45   370.2  1819.6     405 1819.37   409.5 1818.64
     412 1817.38   414.3 1816.48   421.3 1817.49   446.8 1820.32   477.5 1831.68
   521.3 1856.17   532.7 1864.46     542 1867.35   550.4 1873.25   578.8 1888.77
     633 1912.82   667.1 1924.75   676.7 1927.41   715.7 1936.51   744.5 1942.57
#Mann= 5 ,-1 , 0
       0      .1       0     330     .03       0     360      .1       0
     412    .045       0   421.3      .1       0
Bank Sta=412,421.3
XS Rating Curve= 0 ,0
Exp/Cntr=0.3,0.1

Type RM Length L Ch R = 1 ,1719    ,234.4,232,227.4
XS GIS Cut Line= 3
     2122447.819      250422.811     2122750.809      250247.002
     2123263.272      250304.981
#Sta/Elev= 30
       0 1924.71    29.9 1915.43    64.4 1907.52    71.7 1904.63    95.6 1892.53
   102.8 1889.83   124.4 1883.91   139.9 1881.04   219.6 1862.46   249.3  1854.2
   290.1 1841.57   329.6 1832.07   350.3 1823.89   358.7 1822.02   385.1 1818.48
   414.8 1817.49   439.8 1817.59   450.5 1815.27   457.7 1814.93   461.6 1815.14
   470.9 1817.51   484.2 1818.76   521.2 1832.33   563.4 1844.68   622.8 1868.12
     679 1886.23   722.2  1901.5   795.7 1921.56   820.9 1927.43     866 1935.04
#Mann= 5 ,-1 , 0
       0      .1       0     250     .03       0   420.3      .1       0
   450.5    .045       0   461.6      .1       0
Bank Sta=450.5,461.6
XS Rating Curve= 0 ,0
Exp/Cntr=0.3,0.1

Type RM Length L Ch R = 1 ,1487    ,244,243.3,238.8
XS GIS Cut Line= 3
     2122582.481      250647.247     2122840.583      250469.568
     2123281.976       250359.22
#Sta/Elev= 30
       0  1953.3    11.3 1946.48    25.2 1939.62    51.2 1928.76    59.9 1923.22
      76 1916.23   122.9 1898.88   186.9 1879.79     201 1874.69   286.2 1841.46
   327.9 1820.86   343.1  1814.2   347.8 1813.73   351.1 1814.01   361.3  1816.3
   398.2 1816.13   405.2 1817.06   415.4 1822.81   446.9  1836.8   462.7 1845.15
   472.9 1849.33   492.9 1859.43   503.8 1861.62   543.2 1876.21   581.1 1891.65
   601.1 1901.56   641.7 1916.62     710 1935.43   733.3 1940.36   768.3 1945.97
#Mann= 3 ,-1 , 0
       0      .1       0   343.1    .045       0   351.1      .1       0
Bank Sta=343.1,351.1
XS Rating Curve= 0 ,0
Exp/Cntr=0.3,0.1

Type RM Length L Ch R = 1 ,1244    ,189.4,188.2,185.5
XS GIS Cut Line= 2
     2122687.332      250809.168     2123350.692      250472.809
#Sta/Elev= 30
       0  1961.6    36.4  1949.6    80.5  1928.8   106.4 1918.62   128.4 1910.47
   174.8 1895.91   194.5  1886.8   216.3  1878.7   304.9 1836.48   341.7 1816.37
   348.1    1815   363.8  1815.1   371.1 1812.67   374.8 1811.69   377.4 1812.65
   382.1 1814.39   393.2 1814.99   407.9 1818.32   431.1 1827.04     455 1839.21
   476.7 1855.34   514.6 1877.07   540.3  1888.5   572.6 1905.63   585.5 1910.02
   636.3 1932.11   650.7 1937.39   687.5 1946.91   713.2 1955.22   743.8 1961.66
#Mann= 3 ,-1 , 0
       0      .1       0   371.1    .045       0   377.4      .1       0
Bank Sta=371.1,377.4
XS Rating Curve= 0 ,0
Exp/Cntr=0.3,0.1

Type RM Length L Ch R = 1 ,1056    ,246.1,247.1,239.4
XS GIS Cut Line= 2
     2122846.721       251034.43     2123391.276      250528.157
#Sta/Elev= 30
       0 1959.28    45.2 1944.04      73 1932.97    99.9 1924.93   131.9 1911.18
   180.1 1893.52   220.9 1875.93     236    1866   265.7 1853.74   341.8 1815.48
   368.7 1812.08   373.2  1810.9   377.6 1811.86   384.6 1814.04   411.4 1814.02
     421 1815.58   444.9 1825.69   467.3  1837.5   491.4 1853.36   505.4 1864.11
   516.9 1876.36   522.2 1880.37   540.1 1889.87   560.7 1898.53   614.4 1926.25
     642 1935.56   656.2  1941.5   709.2 1953.46   732.8 1961.18   743.5 1963.41
#Mann= 3 ,-1 , 0
       0      .1       0   368.7    .045       0   377.6      .1       0
Bank Sta=368.7,377.6
XS Rating Curve= 0 ,0
Exp/Cntr=0.3,0.1

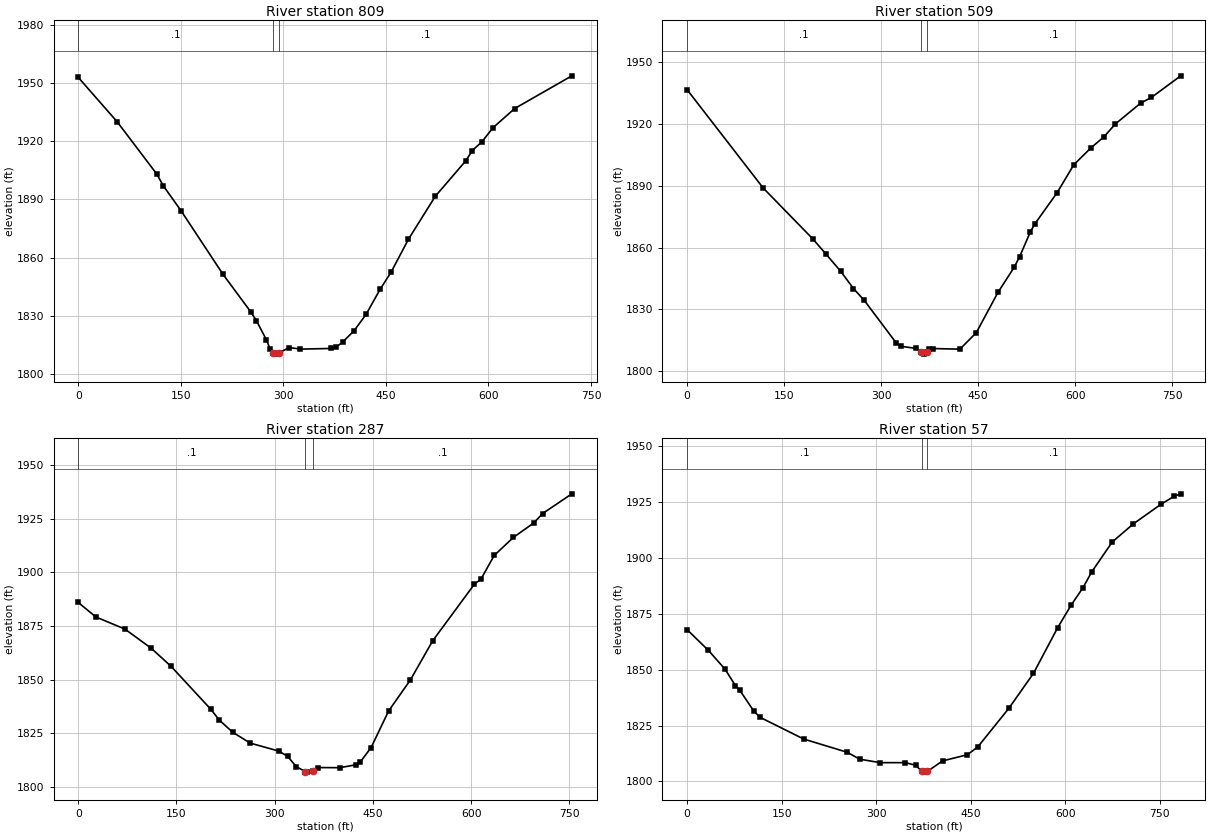
Type RM Length L Ch R = 1 ,809     ,301.1,299.3,287.7
XS GIS Cut Line= 2
     2123044.447      251180.285     2123461.416       250590.97
#Sta/Elev= 30
       0 1952.88      57 1929.97     115 1903.01   124.4 1897.02   150.3 1884.22
   211.5 1851.53   252.5    1832   260.6 1827.55   275.1 1817.76   280.6 1813.02
   284.7    1811   288.7 1810.31   293.9 1811.05   308.8 1813.71   324.9 1812.88
   369.1 1813.23   377.1 1813.88   386.5 1816.44   403.5 1822.39     421 1830.78
   441.4 1843.64   457.5 1852.51     483 1869.52   522.2 1891.61   566.9 1909.93
   576.3 1915.18   590.1 1919.58   606.9 1927.03   638.3 1936.81   721.9 1953.66
#Mann= 3 ,-1 , 0
       0      .1       0   284.7    .045       0   293.9      .1       0
Bank Sta=284.7,293.9
XS Rating Curve= 0 ,0
Exp/Cntr=0.3,0.1

Type RM Length L Ch R = 1 ,509     ,223.7,221.8,216.8
XS GIS Cut Line= 3
     2123387.055       251362.54     2123445.214      251004.984
      2123522.14       250611.48
#Sta/Elev= 30
       0 1936.45   117.6 1888.84   194.1 1864.26     214 1857.08   237.3 1848.55
   257.2 1840.14   273.8 1834.43   323.7 1813.62   330.3 1812.16   353.6 1811.15
  361.11  1809.6   366.9 1808.36   371.4 1809.61   373.6  1810.7   379.8 1811.07
   421.8 1810.76   447.2 1818.79   480.6 1838.26   505.7 1850.43   514.2 1855.63
   530.8 1867.63   537.4 1871.34   572.2 1886.63   597.9  1900.1   624.3 1908.25
   644.4  1913.6   662.2 1919.87   701.2 1929.95   717.9 1932.71   763.2 1943.17
#Mann= 3 ,-1 , 0
       0      .1       0  361.11    .045       0   371.4      .1       0
Bank Sta=361.11,371.4
XS Rating Curve= 0 ,0
Exp/Cntr=0.3,0.1

Type RM Length L Ch R = 1 ,287     ,230.7,230.7,230.7
XS GIS Cut Line= 2
     2123725.238      251352.353     2123566.262      250615.452
#Sta/Elev= 30
       0 1886.01    26.9 1879.24    71.4 1873.56   111.7 1864.58   141.9 1856.17
   202.3 1836.24   215.7 1831.04   235.9 1825.45   262.7 1820.38   306.4 1816.65
   319.8  1814.2   333.3 1809.31   347.1  1807.1   349.9 1806.84   358.7 1807.49
   366.8 1808.97   399.6 1808.91   423.8 1810.26   430.5 1811.47   447.3 1818.29
   474.1  1835.4   507.3 1849.83   541.3 1868.08   605.1 1894.53   615.1 1896.88
   635.3 1907.93   664.6 1916.33   695.7 1923.09   709.1 1927.45   753.9 1936.68
#Mann= 3 ,-1 , 0
       0      .1       0   347.1    .045       0   358.7      .1       0
Bank Sta=347.1,358.7
XS Rating Curve= 0 ,0
Exp/Cntr=0.3,0.1

Type RM Length L Ch R = 1 ,57      ,55.3,52.6,49.2
XS GIS Cut Line= 3
      2123875.18       251293.43     2123844.938      250826.797
     2123641.074      250585.527
#Sta/Elev= 30
       0 1867.89    33.9 1858.59    60.2 1850.22    76.7 1842.88    83.2 1840.97
   106.2 1831.33   116.1 1828.65   185.2 1818.97   254.2 1813.06   273.9 1809.97
   306.8 1808.42   346.3 1808.43   362.8 1807.27   372.6 1804.49   375.8 1804.19
   381.3  1804.5   405.4  1809.2   444.9 1811.97   461.6 1815.53   510.9 1832.81
   549.6 1848.29   588.2 1868.79   609.8 1878.96   628.3 1886.64   642.3 1893.76
   674.9 1907.12   708.5 1915.23   751.7 1923.86   772.9 1927.51   783.5 1928.62
#Mann= 3 ,-1 , 0
       0      .1       0   372.6    .045       0   381.3      .1       0
Bank Sta=372.6,381.3
XS Rating Curve= 0 ,0
Exp/Cntr=0.3,0.1
LCMann Table=0

Chan Stop Cuts=-1
Use User Specified Reach Order=0
Composite Channel Slope=5